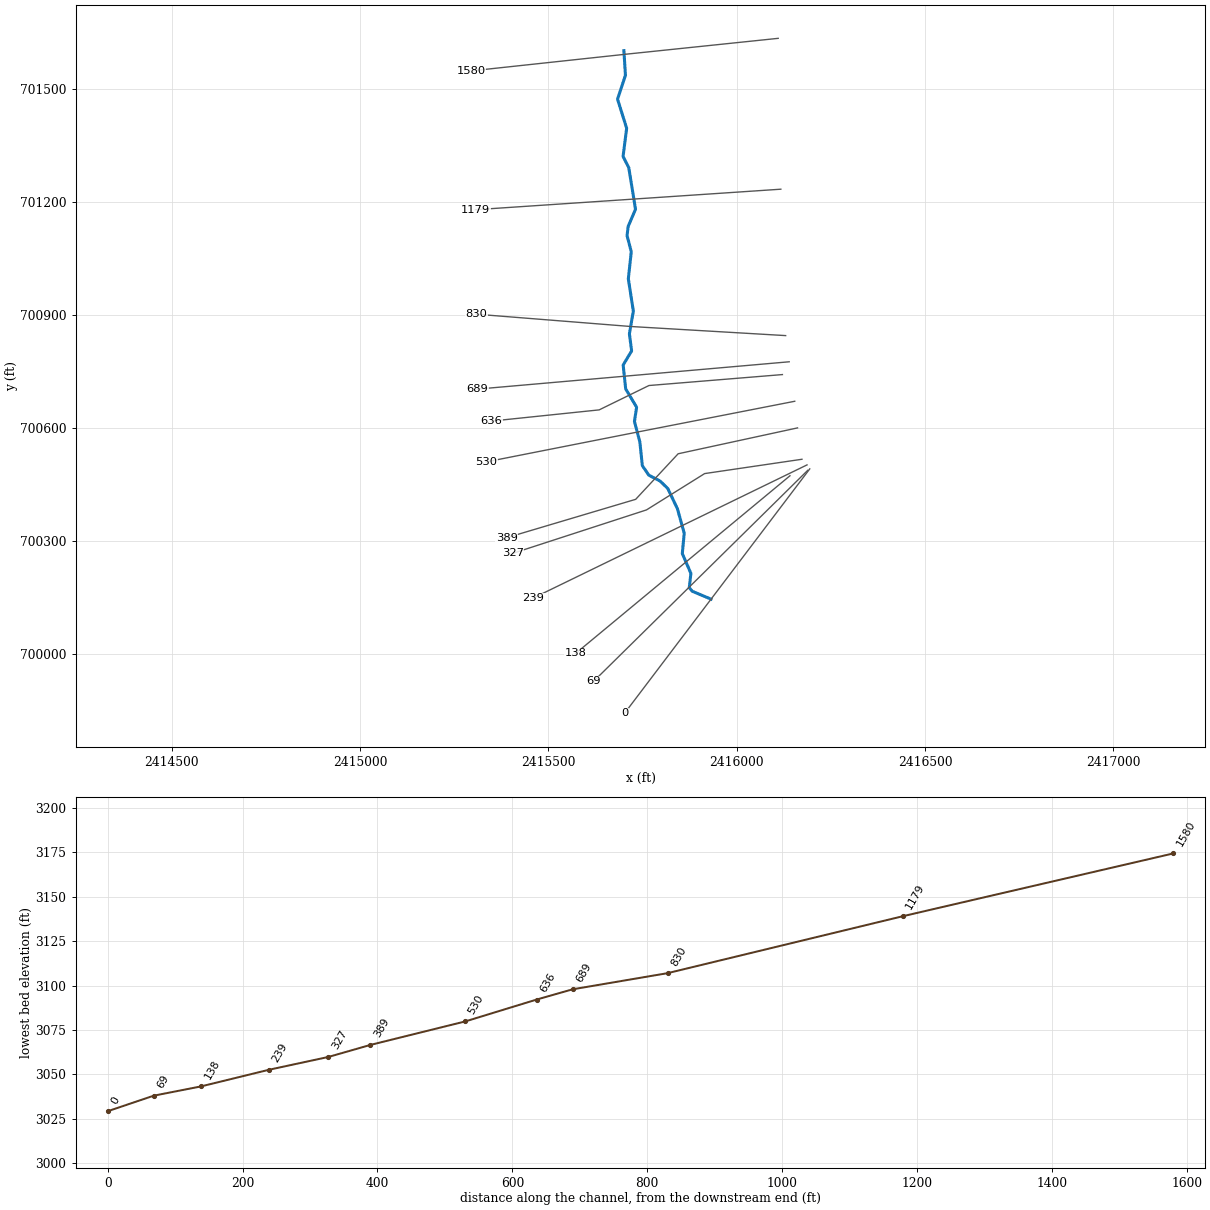
--- NFLONGRN.prj (project) ---

Proj Title=NFLONGRN
Current Plan=p01
Default Exp/Contr=0,0
English Units
Geom File=g01
Flow File=f01
Plan File=p01
BEGIN DESCRIPTION:
Stream Name: North Fork Long Run
Flood Zone: Approximate
Pendleton County, West Virginia
HEC-RAS Version: 5.0.7
Hydrology Method:
Regression equation
END DESCRIPTION:
DSS Export Rating Curves= 0
DSS Export Rating Curve Sorted= 0
DSS Export Volume Flow Curves= 0
DXF OffsetX= 0
DXF OffsetY= 0
DXF ScaleX= 0
DXF ScaleY= 0

--- NFLONGRN.p01 (plan) ---

Plan Title=Floodplain
Program Version=5.07
Short Identifier=Floodplain
Geom File=g01
Flow File=f01
Subcritical Flow
K Sum by GR= 0
Std Step Tol= 0.01
Critical Tol= 0.01
Num of Std Step Trials= 20
Max Error Tol= 0.3
Flow Tol Ratio= 0.001
Split Flow NTrial= 30
Split Flow Tol= 0.02
Split Flow Ratio= 0.02
Log Output Level= 0
Friction Slope Method= 1
Unsteady Friction Slope Method= 2
Unsteady Bridges Friction Slope Method= 1
Parabolic Critical Depth
Global Vel Dist= 0 , 0 , 0
Global Log Level= 0
CheckData=True
Encroach Param=-1 ,0,0, 0
Mapping Interval=1HOUR
Computation Time Step Use Courant=        0
Computation Time Step Use Time Series=    0
Computation Time Step Count To Double=0
Computation Time Step Max Doubling=0
Computation Time Step Max Halving=0
Computation Time Step Residence Courant=0
Run HTab= 0
Run UNet= 0
Run Sediment= 0
Run PostProcess= 0
Run WQNet= 0
Run RASMapper=-1
UNET Theta= 0
UNET Theta Warmup= 0
UNET ZTol= 0
UNET ZSATol= 0
UNET MxIter= 0
UNET Max Iter WO Improvement= 0
UNET MaxInSteps= 0
UNET DtIC= 0
UNET DtMin= 0
UNET MaxCRTS= 0
UNET WFStab= 0
UNET SFStab= 0
UNET WFX= 1
UNET SFX= 1
UNET 1D Methodology=Finite Difference
UNET DSS MLevel= 1
UNET Pardiso=0
UNET DZMax Abort= 0
UNET Use Existing IB Tables= 0
UNET Froude Reduction=False
UNET Froude Limit= 0
UNET Froude Power= 0
UNET D1 Cores= 0
UNET D2 Coriolis=0
UNET D2 Cores= 0
UNET D2 Theta= 1
UNET D2 Theta Warmup= 1
UNET D2 Z Tol= 0.01
UNET D2 Volume Tol= 0.01
UNET D2 Max Iterations= 20
UNET D2 Equation= 0
UNET D2 RampUpFraction=0.1
UNET D2 TimeSlices= 1
UNET D2 BCVolumeCheck=0
UNET D1D2 MaxIter= 0
UNET D1D2 ZTol=0.01
UNET D1D2 QTol=0.1
UNET D1D2 MinQTol=1
Write IC File= 0
Write IC File at Fixed DateTime=0
Write IC File at Sim End=0
Echo Input=False
Echo Parameters=False
Echo Output=False
Write Detailed= 0
HDF Write Warmup=0
HDF Write Time Slices=0
HDF Flush=0
HDF Face Node Velocities=0
HDF Compression= 1
HDF Chunk Size= 1
HDF Spatial Parts= 1
HDF Use Max Rows=0
HDF Fixed Rows= 1
Calibration Method= 0
Calibration Iterations= 20
Calibration Max Change=0.05
Calibration Tolerance=0.2
Calibration Maximum=1.5
Calibration Minimum=0.5
Calibration Optimization Method= 1
WQ AD Non Conservative
WQ ULTIMATE=-1
WQ Max Comp Step=1HOUR
WQ Output Interval=15MIN
WQ Output Selected Increments= 0
WQ Output face flow=0
WQ Output face velocity=0
WQ Output face area=0
WQ Output face dispersion=0
WQ Output cell volume=0
WQ Output cell surface area=0
WQ Output cell continuity=0
WQ Output cumulative cell continuity=0
WQ Output face conc=0
WQ Output face dconc_dx=0
WQ Output face courant=0
WQ Output face peclet=0
WQ Output face adv mass=0
WQ Output face disp mass=0
WQ Output cell mass=0
WQ Output cell source sink temp=0
WQ Output nsm pathways=0
WQ Output nsm derived pathways=0
WQ Output MaxMinRange=-1
WQ Daily Max Min Mean=-1
WQ Daily Range=0
WQ Daily Time=0
WQ Create Restart=0
WQ Fixed Restart=0
WQ System Summary=0
WQ Write To DSS=0
WQ Use Fixed Temperature=0
Sorting and Armoring Iterations= 10
XS Update Threshold= 0.02
Bed Roughness Predictor= 0
Hydraulics Update Threshold= 0.02
Energy Slope Method= 1
Volume Change Method= 1
Sediment Retention Method= 0
XS Weighting Method= 0
Number of US Weighted Cross Sections= 1
Number of DS Weighted Cross Sections= 1
Upstream XS Weight=0
Main XS Weight=1
Downstream XS Weight=0
Number of DS XS's Weighted with US Boundary= 1
Upstream Boundary Weight= 1
Weight of XSs Associated with US Boundary= 0
Number of US XS's Weighted with DS Boundary= 1
Downstream Boundary Weight= 0.5
Weight of XSs Associated with DS Boundary= 0.5
Percentile Method= 0
Sediment Output Level= 3
Mass or Volume Output= 0
Output Increment Type= 1
Profile and TS Output Increment= 1
XS Output Flag= 0
XS Output Increment= 10
Write Gradation File= 0
Read Gradation Hotstart= 0
Write HDF5 File= 1
Write Binary Output= 1
Write DSS Sediment File= 0
SV Curve= 0
Specific Gage Flag= 0

--- NFLONGRN.f01 (steady flow) ---

Flow Title=Flows
Program Version=5.07
Number of Profiles= 6
Profile Names=P100yr,P10yr,P25yr,P50yr,P500yr,P101yr
River Rch & RM=NFLONGRN,Main            ,1580
     584     273     386     482     856     710
River Rch & RM=NFLONGRN,Main            ,0
     807     376     532     665    1187     982
Boundary for River Rch & Prof#=NFLONGRN,Main            , 1
Up Type= 0
Dn Type= 1
Dn Known WS=3032.7
Boundary for River Rch & Prof#=NFLONGRN,Main            , 2
Up Type= 0
Dn Type= 1
Dn Known WS=3031.47
Boundary for River Rch & Prof#=NFLONGRN,Main            , 3
Up Type= 0
Dn Type= 1
Dn Known WS=3031.96
Boundary for River Rch & Prof#=NFLONGRN,Main            , 4
Up Type= 0
Dn Type= 1
Dn Known WS=3032.33
Boundary for River Rch & Prof#=NFLONGRN,Main            , 5
Up Type= 0
Dn Type= 1
Dn Known WS=3033.58
Boundary for River Rch & Prof#=NFLONGRN,Main            , 6
Up Type= 0
Dn Type= 1
Dn Known WS=3033.12
DSS Import GetInterval= 0
DSS Import GetPeak= 0
DSS Import FillOption= 0

--- NFLONGRN.g01 (geometry) ---

Geom Title=Geometry
Program Version=5.07

River Reach=NFLONGRN        ,Main
Reach XY= 30
     2415700.384      701602.116     2415704.451      701536.792
     2415683.503      701473.338     2415707.688      701396.084
     2415698.185      701321.266     2415713.355      701291.252
     2415731.234      701180.933      2415711.67      701135.278
     2415708.796      701110.926     2415719.923      701068.246
     2415712.175      700996.216     2415725.446       700910.38
     2415714.993      700850.268     2415720.882      700804.671
     2415698.399      700767.298     2415705.151      700703.861
     2415734.108      700655.381     2415728.401      700617.236
     2415742.738      700563.101     2415749.314      700500.128
     2415766.498      700474.815     2415796.721      700459.083
     2415816.989      700439.287      2415842.48       700385.68
     2415860.548      700320.642     2415855.433      700266.655
     2415878.273      700213.976     2415873.952      700175.909
     2415881.947       700166.63     2415931.719      700145.547

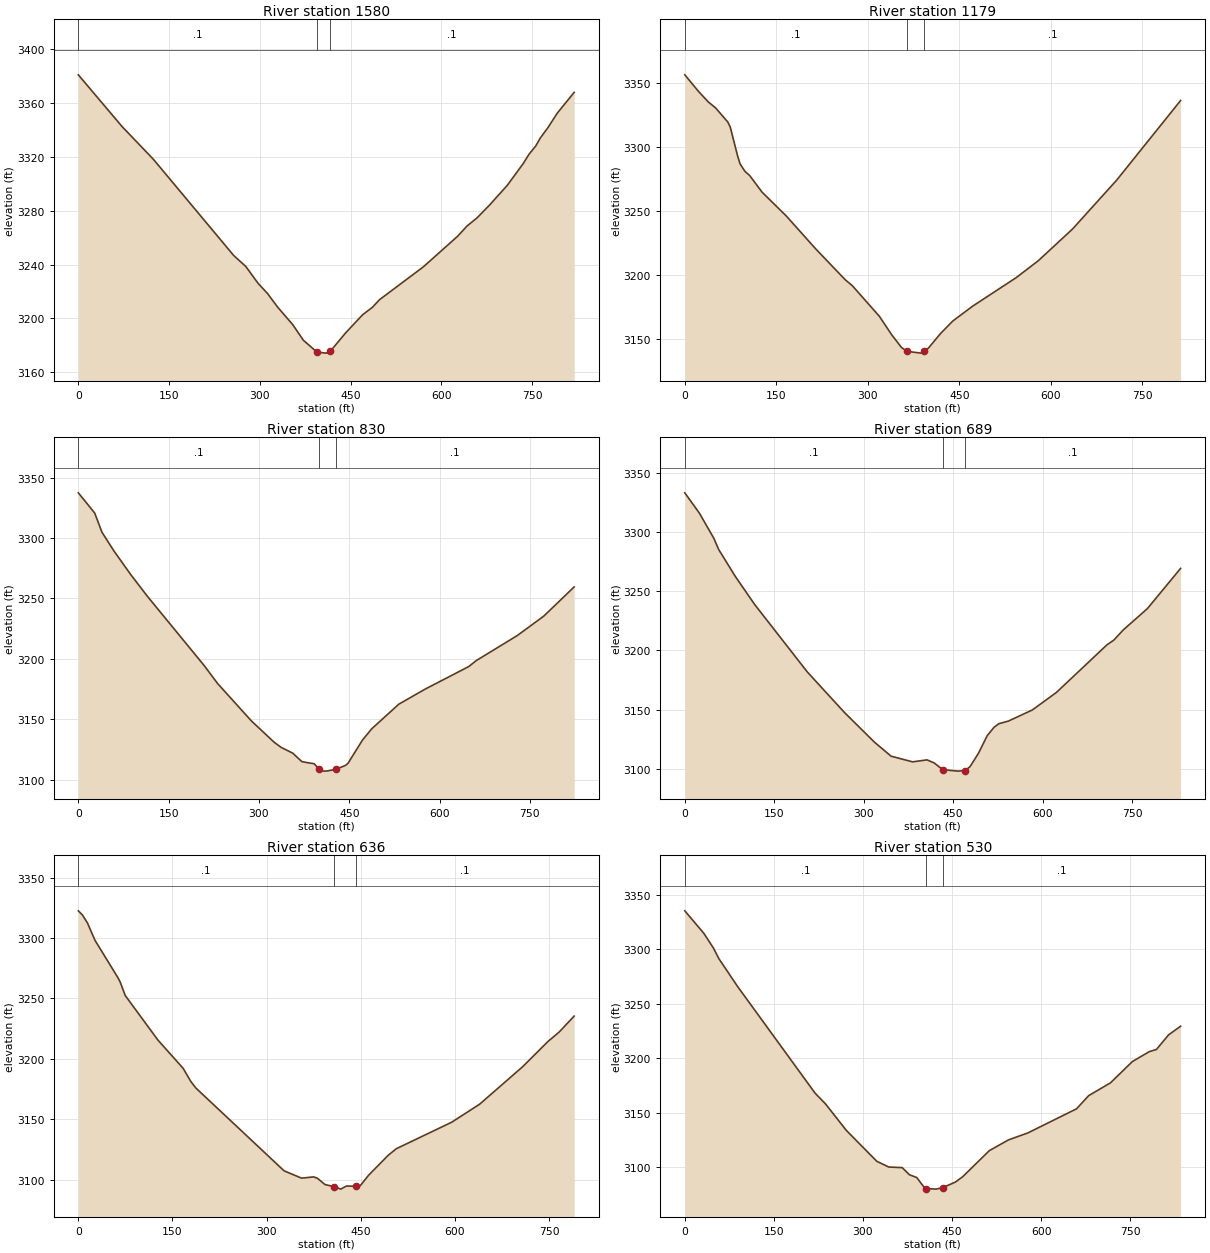
Type RM Length L Ch R = 1 ,1580    ,397.5,401.5,400.6
XS GIS Cut Line= 3
     2416110.069      701634.845     2415702.408      701592.346
2415295.27468196701548.434204999
#Sta/Elev= 30
       0 3380.93    72.2 3342.56     124 3318.22   256.7  3246.8   276.8  3238.6
   296.9 3226.19   312.6 3218.58   329.1 3208.57     354  3195.6   371.9 3183.83
   394.4 3175.02   409.5 3174.26   416.23175.521   441.7 3189.28   469.9 3202.77
     486 3208.29     498 3214.03   570.5 3238.45   626.8 3261.04   642.3 3268.62
     659 3274.74   679.1 3283.99   708.7 3298.76   735.4 3315.14     745 3322.07
   755.9 3328.08   763.6  3334.1   775.6 3341.41   791.7 3352.58   819.4  3367.9
#Mann= 3 ,-1 , 0
       0      .1       0   394.4    .045       0   416.2      .1       0
Bank Sta=394.4,416.2
XS Rating Curve= 0 ,0
Exp/Cntr=0.3,0.1

Type RM Length L Ch R = 1 ,1179    ,348,348.5,345.9
XS GIS Cut Line= 2
2416117.10501899701234.231338301     2415306.082      701179.759
#Sta/Elev= 30
       0 3356.32    22.4 3343.43    38.4  3335.2    50.5 3330.47    70.5 3319.46
    74.5 3315.58    86.6 3292.92    90.6 3286.79    98.6 3280.93   106.6 3277.53
   126.6 3264.72   166.6 3245.95   214.8 3220.28     263 3196.27     275 3191.46
   319.1 3167.64   339.1 3153.34   355.2 3143.38   364.2 3140.33   387.2 3138.93
   392.3  3140.3   399.3 3142.78   419.3 3154.25   439.3 3163.96   471.4 3175.45
   543.6 3197.98   579.7 3211.18   635.8 3235.92     708 3274.02   812.9 3336.27
#Mann= 3 ,-1 , 0
       0      .1       0   364.2    .045       0   392.3      .1       0
Bank Sta=364.2,392.3
XS Rating Curve= 0 ,0
Exp/Cntr=0.3,0.1

Type RM Length L Ch R = 1 ,830     ,139.9,140.8,144.4
XS GIS Cut Line= 3
     2416129.856      700845.446     2415718.427      700869.638
     2415308.414      700902.303
#Sta/Elev= 30
       0 3337.32    27.2  3320.6    39.2 3304.74    59.2 3289.16    87.3 3269.48
   115.3 3251.31   208.7 3194.54   231.5 3179.36   287.6 3148.43   325.3 3130.83
   337.3 3126.48   356.3 3121.77   371.4 3114.75   391.8 3113.06   399.8  3108.5
   403.8 3107.07   411.8 3106.95   427.9 3108.47   427.9 3108.48   443.9 3111.72
   447.9 3113.45     472 3132.68   487.3 3141.99   532.2 3162.34   576.3  3174.9
   648.6 3193.55   660.6 3198.35   728.8  3219.1     773 3235.24   823.5 3259.43
#Mann= 3 ,-1 , 0
       0      .1       0   399.8    .045       0   427.9      .1       0
Bank Sta=399.8,427.9
XS Rating Curve= 0 ,0
Exp/Cntr=0.3,0.1

Type RM Length L Ch R = 1 ,689     ,49.9,53.1,63.1
XS GIS Cut Line= 2
2416139.28024127700775.9353774492415311.13380914700703.315454227
#Sta/Elev= 30
       0 3333.29    24.6 3316.01    48.7 3294.81    56.8 3285.36    84.9 3262.42
     117 3238.93   205.3 3181.84   267.9 3147.36   317.7 3122.51   345.9  3110.5
     382 3105.71   406.1  3107.4   418.1 3104.81   432.53099.104   458.3 3097.87
   470.3  3098.4   470.3 3098.41   478.4 3101.76   492.4 3113.01   507.2 3128.02
   518.5 3134.96   526.5 3137.97   542.6 3140.22   582.8 3149.64   622.9 3164.37
     708  3204.8   719.3 3208.69   735.3 3217.41   775.5  3235.3   831.3 3269.38
#Mann= 3 ,-1 , 0
       0      .1       0   432.5    .045       0   470.3      .1       0
Bank Sta=432.5,470.3
XS Rating Curve= 0 ,0
Exp/Cntr(USF)=0,0
Exp/Cntr=0.3,0.1

Type RM Length L Ch R = 1 ,636     ,107.2,106,113
XS GIS Cut Line= 4
2416121.20091513700741.9529344722415766.94990195700712.900249008
2415634.71280497700648.2128379282415349.05777727700618.445179731
#Sta/Elev= 30
       0 3322.54     6.5 3319.13    14.5 3312.54    26.5 3298.16    62.7 3267.51
    66.7 3263.56    74.7 3252.44   126.9 3215.48     167 3192.14   179.1 3181.35
   187.3 3175.81   327.8 3107.28   355.7 3101.22     375 3102.27     381 3101.08
     393 3095.91   407.23094.232     418 3092.13   426.9 3094.67   441.73094.556
   449.2 3095.02   462.5 3103.67   493.7 3120.16   506.6 3125.59   594.9 3147.55
   639.4 3162.48   707.8 3193.45   747.9 3214.23   766.1 3222.23   789.9 3235.39
#Mann= 3 , 0 , 0
       0      .1       0   407.2    .045       0   441.7      .1       0
Bank Sta=407.2,441.7
XS Rating Curve= 0 ,0
Exp/Cntr(USF)=0,0
Exp/Cntr=0.3,0.1

Type RM Length L Ch R = 1 ,530     ,130.6,140.7,147.1
XS GIS Cut Line= 3
2416153.97636985 700671.08311236     2415736.087      700589.295
     2415334.821      700510.091
#Sta/Elev= 30
       0  3335.1    31.8 3314.65    48.1 3301.08    57.5 3291.13    88.9 3265.68
   219.3 3167.91     237 3157.95   271.7 3133.87   323.3 3105.33   343.4  3100.1
     366 3099.55   378.3 3092.98   390.5 3090.48   402.7 3081.69   406.8 3080.33
   423.1 3079.82   434.6 3081.26   455.7 3086.33     468 3091.26   512.8 3115.15
   544.8 3124.93     578 3131.47   659.6  3153.5     680 3165.58   716.7 3177.31
   753.4 3196.76   781.9 3205.91   794.1 3207.92   814.5 3221.32   834.8 3229.26
#Mann= 3 ,-1 , 0
       0      .1       0   406.8    .045       0   434.6      .1       0
Bank Sta=406.8,434.6
XS Rating Curve= 0 ,0
Exp/Cntr=0.3,0.1

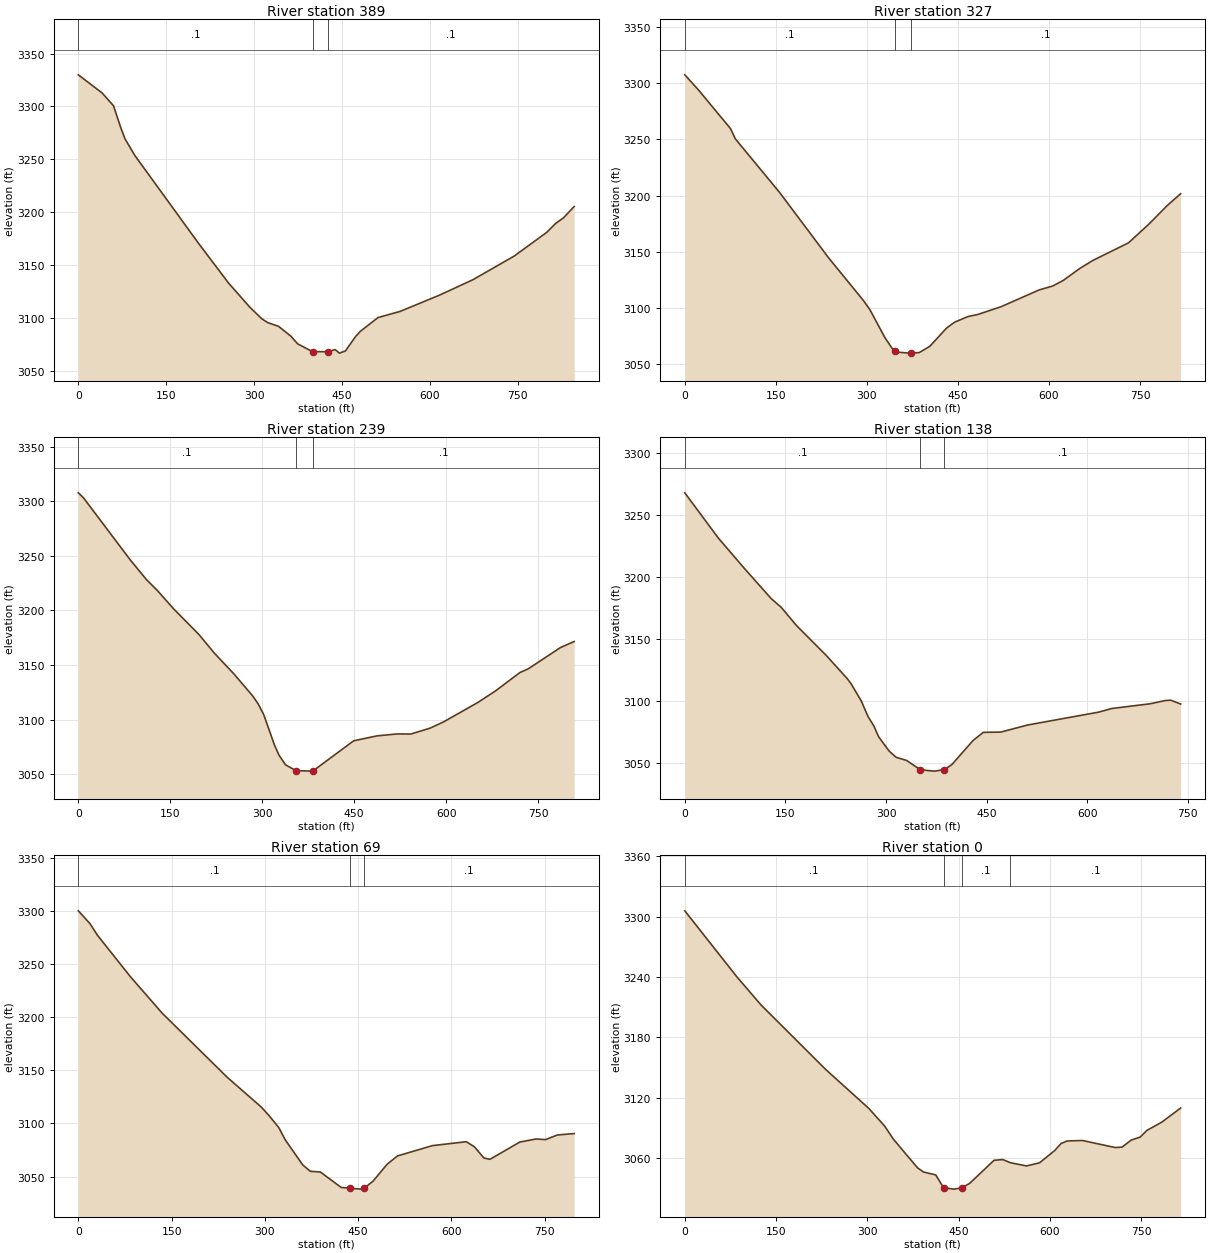
Type RM Length L Ch R = 1 ,389     ,66.6,62,60.2
XS GIS Cut Line= 4
2416161.39601781700600.3554900432415844.36731892700531.635396352
2415731.66636526700410.6880314542415389.89843264700308.982292791
#Sta/Elev= 30
       0 3329.89    40.5 3312.79      60 3300.65    72.3 3280.07    79.9 3269.08
    96.8 3253.32   205.3 3170.39   256.5 3132.84   292.7  3110.1   312.9 3099.22
     323 3095.56   341.8 3091.96   362.9 3082.58   374.2 3075.49   399.7 3067.97
   426.5 3067.97   438.3 3069.95   445.7 3066.61   455.9 3068.69   473.2  3082.3
   481.7 3087.38   511.5 3100.25   549.1 3106.05   615.9 3121.31   673.6 3136.08
   744.4 3158.59   799.5 3180.86   815.1 3189.48     828 3194.55   846.3 3205.29
#Mann= 3 ,-1 , 0
       0      .1       0   399.7    .045       0   426.5      .1       0
Bank Sta=399.7,426.5
XS Rating Curve= 0 ,0
Exp/Cntr(USF)=0,0
Exp/Cntr=0.3,0.1

Type RM Length L Ch R = 1 ,327     ,91.1,88,88.4
XS GIS Cut Line= 4
2416173.16791865 700517.081950692415914.77105056700479.055761731
2415760.30817213700382.5631462692415405.08654228700267.087865008
#Sta/Elev= 30
       0 3307.44    22.7 3293.89    75.2 3259.67    83.3 3250.45   156.1 3202.84
   236.9 3144.62   294.2 3106.71   304.9 3098.57   329.4  3073.9   341.4 3064.21
   345.73061.945   351.3 3060.69   369.7 3059.87   373.23059.983   386.1 3060.32
   403.6  3065.9     431 3082.02   444.3 3087.36   466.5  3092.4   482.8 3094.26
   520.7 3101.09   583.7 3116.08   606.2 3119.59   623.4 3124.52     651 3135.31
   672.1 3142.29     731 3157.99   764.9 3174.81   795.2 3191.39   816.8 3201.66
#Mann= 3 , 0 , 0
       0      .1       0   345.7    .045       0   373.2      .1       0
Bank Sta=345.7,373.2
XS Rating Curve= 0 ,0
Exp/Cntr(USF)=0,0
Exp/Cntr=0.3,0.1

Type RM Length L Ch R = 1 ,239     ,100.8,101,111.4
XS GIS Cut Line= 2
2416186.58425874700502.1090948332415459.25078711700148.338052509
#Sta/Elev= 30
       0  3307.8     8.3 3303.31    84.3 3246.63     111 3228.33   128.8 3218.34
   155.5 3201.41   196.8 3177.89   222.2 3160.65   253.4 3142.07   284.5 3121.55
   293.4 3114.27   302.3 3104.67   320.1 3076.37   327.4 3067.25   337.9  3058.5
   354.9 3053.13   382.4 3052.68   382.4  3052.7   449.1 3080.46   487.1 3084.99
   520.2 3086.77   542.5 3086.69   573.9 3092.09   595.9 3097.85   651.7 3115.61
   680.4 3126.16   720.4 3143.08   733.8 3146.41   786.3  3165.9   808.8 3171.52
#Mann= 3 ,-1 , 0
       0      .1       0   354.9    .045       0   382.4      .1       0
Bank Sta=354.9,382.4
XS Rating Curve= 0 ,0
Exp/Cntr(USF)=0,0
Exp/Cntr=0.3,0.1

Type RM Length L Ch R = 1 ,138     ,71.8,69.9,65.6
XS GIS Cut Line= 2
 2416141.2834742700473.2545884122415572.14690027700001.342648898
#Sta/Elev= 30
       0 3268.02    50.1 3231.44    88.7 3207.09     129 3182.51   143.6 3175.67
   166.6 3160.83   210.9 3136.73   242.3 3117.93   247.8 3113.99   263.1    3100
   273.2 3087.41   281.9 3079.78   289.1 3070.97   304.6 3059.57   315.1 3054.47
   330.7 3051.94   351.4 3044.36   372.2  3043.3     387 3044.48   398.2 3048.58
   429.8 3068.02     445 3074.61     471 3074.81   511.3 3080.55   617.1 3090.94
   636.6 3093.86   693.8 3097.67   716.5  3100.3   724.4 3100.62   739.3 3097.47
#Mann= 3 ,-1 , 0
       0      .1       0   351.4    .045       0     387      .1       0
Bank Sta=351.4,387
XS Rating Curve= 0 ,0
Exp/Cntr(USF)=0,0
Exp/Cntr=0.3,0.1

Type RM Length L Ch R = 1 ,69      ,69,68.5,68.9
XS GIS Cut Line= 2
 2416188.4928795700487.7014429642415620.40677165699927.861746355
#Sta/Elev= 30
       0 3300.32    18.8 3288.19    30.5 3277.53    83.8 3238.24   134.7 3204.02
   239.4 3143.53   294.5 3115.34   307.3 3107.05   322.6 3095.98   332.7 3084.69
     361 3060.92   373.1 3054.94   389.3 3054.25   422.9 3039.67   437.4    3039
   454.4 3038.11     460 3038.99   474.2 3045.68   496.9 3061.67   513.5 3069.39
   569.7 3079.11   624.1 3082.78   637.1 3078.04   652.4 3067.41   662.2 3066.22
   710.1 3082.43   736.3 3085.37   751.4 3084.75   770.5 3089.12   797.6 3090.46
#Mann= 3 ,-1 , 0
       0      .1       0   437.4    .045       0     460      .1       0
Bank Sta=437.4,460
XS Rating Curve= 0 ,0
Exp/Cntr(USF)=0,0
Exp/Cntr=0.3,0.1

Type RM Length L Ch R = 1 ,0       ,,,
XS GIS Cut Line= 2
2416193.84784425700491.5213236432415701.93812368 699842.26758208
#Sta/Elev= 30
       0 3305.74    86.1  3239.8   125.4 3212.14   231.6 3148.12   302.5 3109.41
   328.2 3092.09   342.9 3078.82   382.4 3050.48   392.2 3046.37   412.3 3043.45
   425.2 3030.68   442.3 3029.35   455.5 3030.65   468.1 3035.13     508 3057.95
   522.3 3058.73     535 3055.56   561.5 3052.37   582.9 3055.51     608 3067.82
   618.1 3074.64   628.1 3077.16   653.2 3077.67   707.2 3070.64   718.4 3071.09
   733.5  3078.1   747.9 3080.96   759.3 3087.71   783.7 3095.88   814.6 3109.91
#Mann= 4 ,-1 , 0
       0      .1       0   425.2    .045       0   455.5      .1       0
     535      .1       0
Bank Sta=425.2,455.5
XS Rating Curve= 0 ,0
Exp/Cntr(USF)=0,0
Exp/Cntr=0.3,0.1
LCMann Table=0

Chan Stop Cuts=-1
Use User Specified Reach Order=0
Composite Channel Slope=5